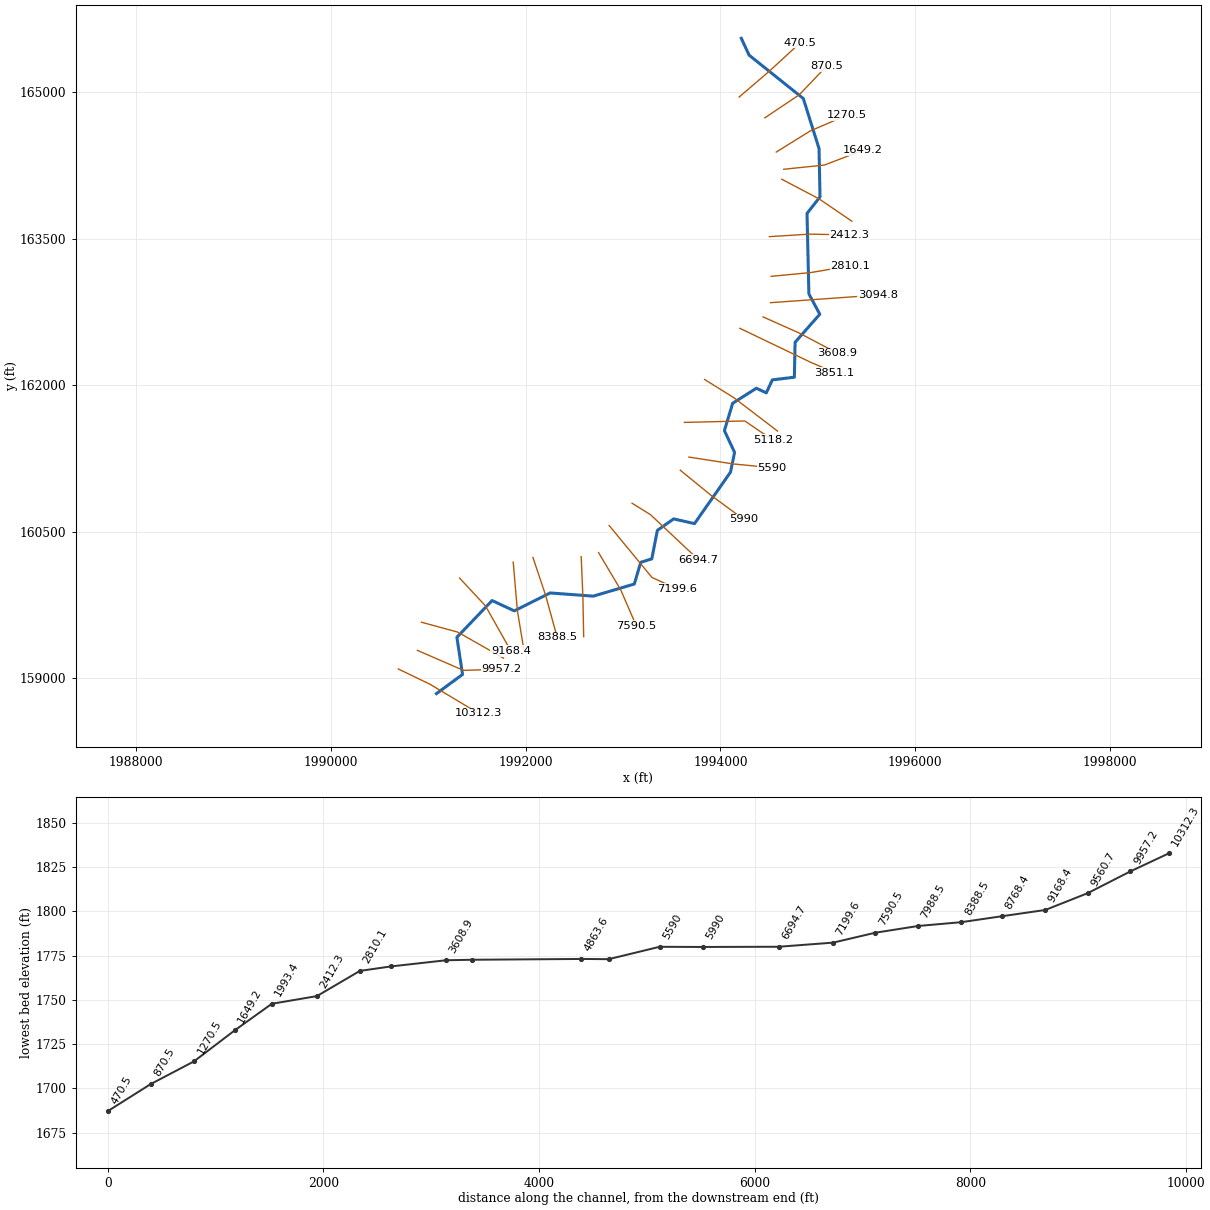
--- LttlIslnd.prj (project) ---

Proj Title=LttlIslnd
Current Plan=p01
Default Exp/Contr=0,0
English Units
Geom File=g01
Flow File=f01
Plan File=p01
BEGIN DESCRIPTION:
END DESCRIPTION:
DSS Export Rating Curves= 0
DSS Export Rating Curve Sorted= 0
DSS Export Volume Flow Curves= 0
DXF OffsetX= 0
DXF OffsetY= 0
DXF ScaleX= 0
DXF ScaleY= 0

--- LttlIslnd.p01 (plan) ---

Plan Title=Floodplain
Program Version=4.00
Geom File=g01
Flow File=f01
K Sum by GR=0
Std Step Tol=0.01
Critical Tol=0.01
Num of Std Step Trials=20
Max Error Tol=0.3
Flow Tol Ratio=0.001
Split Flow NTrial=30
Split Flow Tol=0.02
Split Flow Ratio=0.02
Log Output Level=0
Friction Slope Method=1
Unsteady Friction Slope Method=2
Unsteady Bridges Friction Slope Method=1
Global Log Level=0
CheckData=False
Run HTab=0
Run UNet=0
Run PostProcess=0
UNET Theta=0
UNET Theta Warmup=0
UNET ZTol=0
UNET ZSATol=0
UNET MxIter=0
UNET MaxInSteps=0
UNET DtIC=0
UNET DtMin=0
UNET MaxCRTS=0
UNET WFStab=0
UNET SFStab=0
UNET WFX=0
UNET SFX=0
UNET DSS MLevel=0
UNET DZMax Abort=0
UNET Convert EG Bridges=0
UNET Use Existing IB Tables=0
UNET Froude Limit=0
UNET Froude Power=0
Write IC File=0
Echo Input=False
Echo Output=False
Write Detailed=0

--- LttlIslnd.f01 (steady flow) ---

Flow Title=NFF Regression Equation
Program Version=4.00
Number of Profiles=1
Profile Names=P100yr
River Rch & RM=LttlIslnd,Main      ,10312.3
523.3031
River Rch & RM=LttlIslnd,Main      ,8388.5
564.1575
River Rch & RM=LttlIslnd,Main      ,7199.6
600.3024
River Rch & RM=LttlIslnd,Main      ,6694.7
711.4256
River Rch & RM=LttlIslnd,Main      ,5118.2
753.1412
River Rch & RM=LttlIslnd,Main      ,470.5
827.5580
Boundary for River Rch & Prof#=LttlIslnd,Main      ,1
Up Type=0
Dn Type=3
Dn Slope=0.03809

--- LttlIslnd.g01 (geometry) ---

Geom Title=USGS 3m DEM
Program Version=4.10

River Reach=LttlIslnd       ,Main
Reach XY= 30
     1991083.472      158843.007     1991351.423       159039.28
     1991293.644      159419.891     1991655.027      159795.789
      1991883.45       159689.83     1992250.638      159873.423
     1992694.648      159840.871     1993115.559      159964.877
     1993181.627      160187.225     1993294.909      160222.382
       1993352.2      160514.048     1993519.276      160631.461
     1993733.711      160583.059     1994103.502      161110.402
     1994145.169      161312.225     1994040.668      161535.122
     1994125.638       161814.83     1994368.725      161968.621
      1994470.69        161921.6      1994533.19      162054.413
     1994759.031      162081.636     1994766.553      162439.146
     1995020.169      162726.288      1994908.19      162934.621
     1994889.097      163757.683     1995022.457      163927.264
     1995012.578      164421.187     1994850.857      164934.245
     1994294.326      165378.041     1994214.158      165550.052

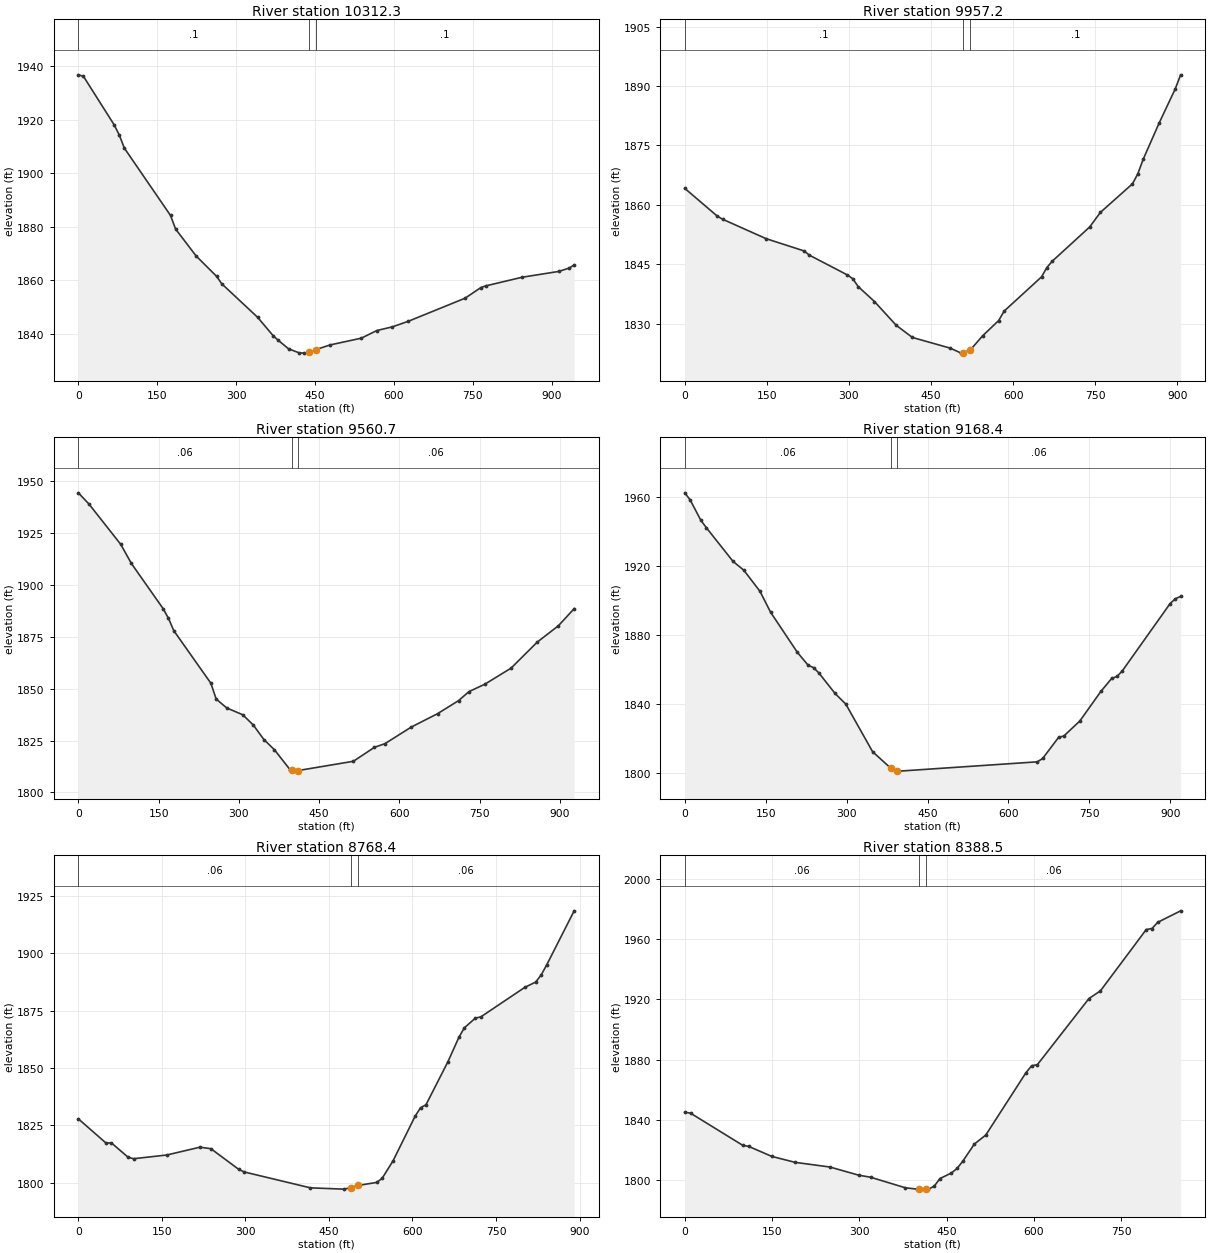
Type RM Length L Ch R = 1 ,10312.3 ,353.5,355.1,367.2
XS GIS Cut Line= 3
     1990691.844      159095.319     1991016.736      158939.458
     1991516.964       158640.93
#Sta/Elev= 30
       0 1936.79     9.7 1936.24    68.2 1918.07    77.9 1914.26    87.6 1909.36
   175.3 1884.21     185 1879.12     224 1869.06     263 1861.43   272.7 1858.67
   340.9 1846.14   370.2 1839.31   380.1 1837.53   399.8 1834.34   419.6 1832.86
   429.5 1832.73   439.3 1833.04   451.3 1834.01   478.8  1835.8   538.1 1838.32
   567.7 1841.18   597.3 1842.56   626.9 1844.59   735.5 1853.27   765.2 1857.21
     775 1857.89   844.1 1861.11   913.3 1863.27     933  1864.5   942.9 1865.69
#Mann= 3 , 0 , 0
       0      .1       0   439.3    .045       0   451.3      .1       0
Bank Sta=439.3,451.3
XS Rating Curve= 0 ,0
Exp/Cntr=0.3,0.1

Type RM Length L Ch R = 1 ,9957.2  ,397.1,396.5,384.6
XS GIS Cut Line= 3
     1990888.139      159285.862     1991360.652       159081.01
     1991751.559      159093.807
#Sta/Elev= 30
       0 1864.16    59.4 1857.15    69.3 1856.36   148.6 1851.47   217.9 1848.38
   227.8  1847.3   297.1 1842.32     307 1841.36   316.9 1839.38   346.6 1835.61
   386.3 1829.62     416 1826.54   485.3 1823.84   505.1 1822.59     509 1822.66
     521 1823.26   544.3 1826.97   573.7 1830.82   583.4 1833.17   651.9 1841.83
   661.7 1844.19   671.4 1845.77   739.9 1854.42   759.5  1858.1   818.1 1865.31
   827.9 1867.84   837.7 1871.51     867  1880.7   896.4  1889.3   906.1 1892.81
#Mann= 3 , 0 , 0
       0      .1       0     509    .045       0     521      .1       0
Bank Sta=509,521
XS Rating Curve= 0 ,0
Exp/Cntr=0.3,0.1

Type RM Length L Ch R = 1 ,9560.7  ,399,392.2,380.8
XS GIS Cut Line= 3
      1990929.62      159573.967     1991302.494      159472.521
     1991772.572      159206.273
#Sta/Elev= 30
       0 1944.39    19.8 1939.01    79.3 1919.55    99.1 1910.37   158.5 1888.56
   168.4 1883.96   178.4 1877.97   247.7 1852.65   257.6 1845.03   277.4 1840.72
   307.2 1837.46     327  1832.5   346.8 1825.51   366.6 1820.55   396.2 1810.81
   399.2 1810.65   406.1 1810.28   411.2 1810.58   514.1 1815.03   553.4 1821.75
   573.1 1823.52   622.2  1831.5   671.3 1837.95   710.6 1844.25   730.2 1848.61
   759.7 1852.16   808.8 1859.92   857.9  1872.5   897.2 1880.31   926.7 1888.59
#Mann= 3 , 0 , 0
       0     .06       0   399.2    .045       0   411.2     .06       0
Bank Sta=399.2,411.2
XS Rating Curve= 0 ,0
Exp/Cntr=0.3,0.1

Type RM Length L Ch R = 1 ,9168.4  ,413.2,399.9,393.3
XS GIS Cut Line= 3
     1991321.305      160025.516     1991586.251      159742.059
     1991848.224      159279.801
#Sta/Elev= 30
       0 1962.35      10 1958.19    29.8 1946.39    39.8 1942.18    89.5 1922.54
   109.4 1917.44   139.3 1905.22   159.2 1892.98   208.9 1869.67   228.8 1862.23
   238.8 1860.88   248.7 1857.75   278.6 1845.89   298.5 1839.71   348.2 1812.08
     382 1802.48     394 1801.01   397.8  1800.8   653.7  1806.2   663.5 1808.14
     693 1820.38   702.9 1821.23   732.4  1829.9   771.7 1847.17   791.4 1854.57
   801.3 1855.75   811.1 1858.95   899.6 1897.98   909.5 1900.87   919.3 1902.18
#Mann= 3 , 0 , 0
       0     .06       0     382    .045       0     394     .06       0
Bank Sta=382,394
XS Rating Curve= 0 ,0
Exp/Cntr=0.3,0.1

Type RM Length L Ch R = 1 ,8768.4  ,375.9,379.7,386.8
XS GIS Cut Line= 3
     1991872.022      160188.268     1991914.569      159693.979
       1991979.1      159305.117
#Sta/Elev= 30
       0 1827.87    49.6 1817.36    59.5 1817.38    89.3 1811.17    99.2 1810.51
   158.8 1812.13   218.3 1815.53   238.1 1814.87   287.8 1805.92   297.7 1804.76
   416.7 1797.84   476.3 1797.28   490.1 1797.92   502.1 1798.88   535.5 1800.19
   545.4 1801.93   565.1  1809.6   604.5 1828.91   614.4 1832.69   624.2 1833.98
   663.6 1852.71   683.4 1863.37   693.2  1867.5   712.9  1871.7   722.8 1872.25
   801.6 1885.07   821.3 1887.41   831.2 1890.53     841 1894.86   890.3 1918.39
#Mann= 3 , 0 , 0
       0     .06       0   490.1    .045       0   502.1     .06       0
Bank Sta=490.1,502.1
XS Rating Curve= 0 ,0
Exp/Cntr=0.3,0.1

Type RM Length L Ch R = 1 ,8388.5  ,405.8,400,395.7
XS GIS Cut Line= 3
       1992074.7      160236.594     1992204.879      159848.954
     1992322.759      159421.696
#Sta/Elev= 30
       0 1845.06      10 1844.37    99.7 1822.99   109.7 1822.32   149.6 1815.64
   189.5 1811.71   249.3  1808.6   299.2 1803.14   319.2 1801.82     379  1794.8
   398.9  1793.9   402.9  1793.9   414.9 1793.91   418.8 1793.91   428.6 1795.84
   438.5 1800.92   458.2 1804.64     468 1807.66   477.9 1812.56   497.6 1823.85
   517.3 1829.88   586.2 1871.23     596  1875.9   605.9 1876.63   694.6 1920.62
   714.2 1925.68     793 1966.46   802.9 1967.16   812.7 1971.26   852.1 1978.91
#Mann= 3 , 0 , 0
       0     .06       0   402.9    .045       0   414.9     .06       0
Bank Sta=402.9,414.9
XS Rating Curve= 0 ,0
Exp/Cntr=0.3,0.1

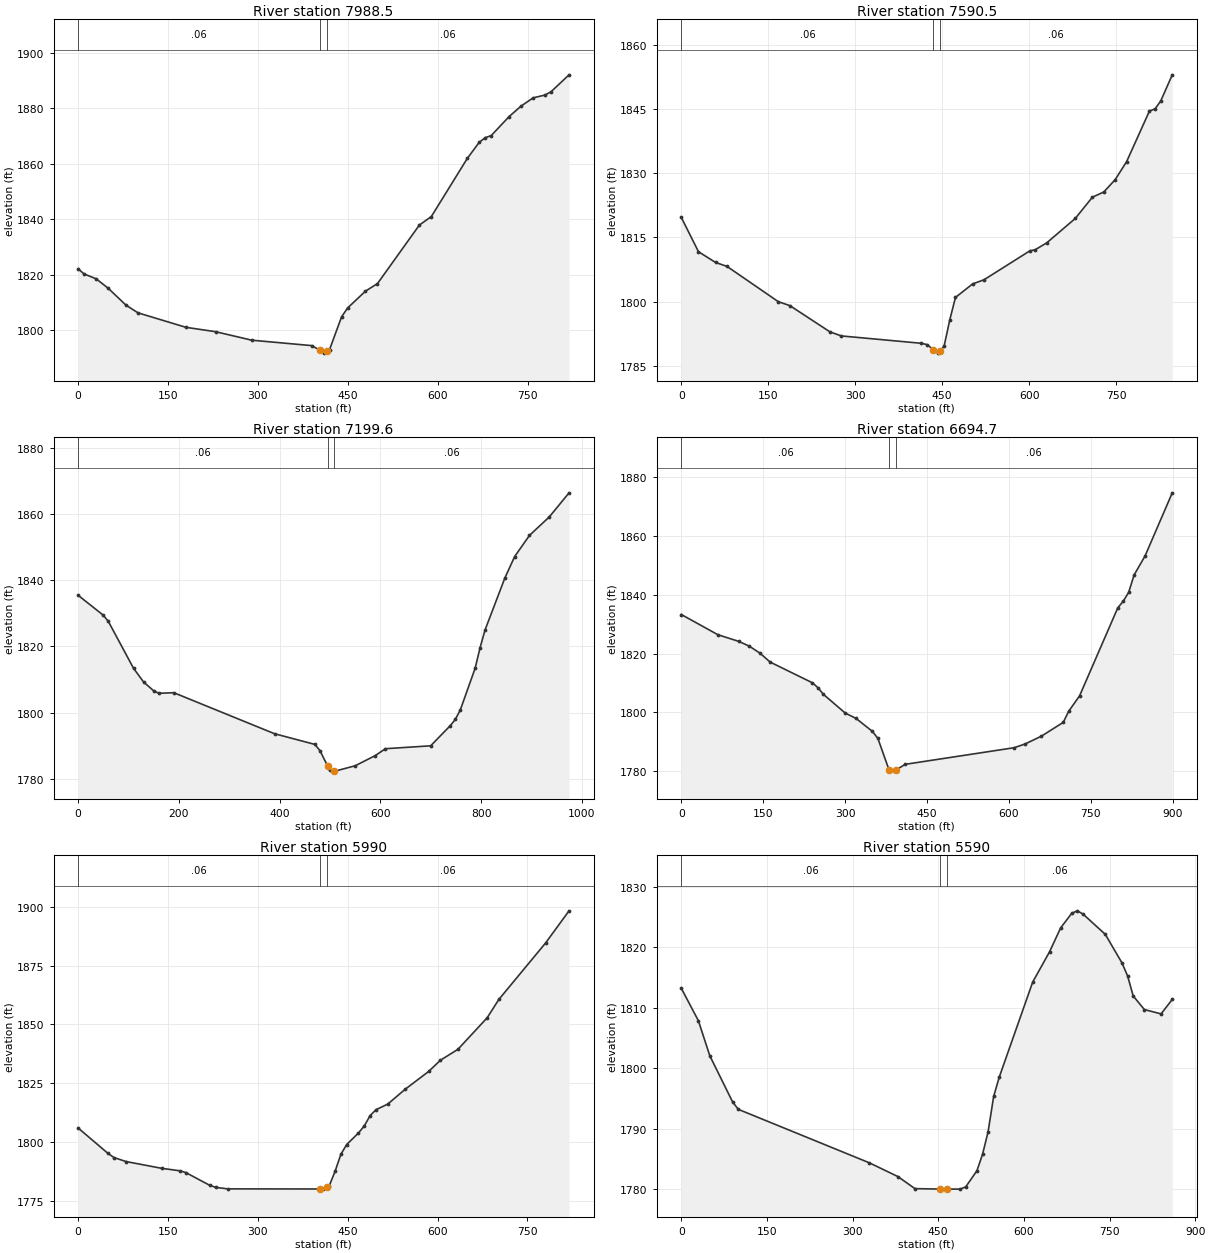
Type RM Length L Ch R = 1 ,7988.5  ,387.6,398.1,406.5
XS GIS Cut Line= 3
     1992570.049      160244.925     1992587.407      159835.666
     1992595.513      159426.269
#Sta/Elev= 30
       0 1822.13      10 1820.26      30 1818.53      50 1815.16    79.9 1809.03
    99.9 1806.26   179.8 1801.05   229.8 1799.45   289.7 1796.41   389.6 1794.46
   403.6 1792.81   409.6 1791.75   415.6 1792.53   419.6 1793.05   439.6 1804.81
   449.6 1807.99   479.5 1814.08   499.5 1816.79   569.4 1837.87   589.4 1840.94
   649.3 1861.85   669.3 1867.68   679.3 1869.33   689.3  1870.1   719.2 1876.96
   739.2 1880.73   759.2 1883.68   779.2  1884.7   789.1 1885.89   819.1 1891.97
#Mann= 3 , 0 , 0
       0     .06       0   403.6    .045       0   415.6     .06       0
Bank Sta=403.6,415.6
XS Rating Curve= 0 ,0
Exp/Cntr=0.3,0.1

Type RM Length L Ch R = 1 ,7590.5  ,387.5,390.6,396.1
XS GIS Cut Line= 3
     1992748.257      160286.467     1992975.621      159905.685
     1993136.453      159535.623
#Sta/Elev= 30
       0 1819.65    29.6 1811.64    59.1 1809.13    78.8 1808.21   167.5 1799.95
   187.2 1799.05   256.2 1792.93     276 1791.96   413.9 1790.24   423.8 1789.94
   434.9 1788.77   443.5 1787.94   446.9 1788.49   453.3 1789.53   463.2 1795.74
     473 1800.96   502.6 1804.12   522.2 1805.08     601 1811.82   610.8 1812.12
   630.5 1813.72   679.7 1819.42   709.2 1824.38   728.9  1825.6   748.6  1828.5
   768.3 1832.71   807.6 1844.51   817.5 1845.04   827.3 1846.93     847 1852.98
#Mann= 3 , 0 , 0
       0     .06       0   434.9    .045       0   446.9     .06       0
Bank Sta=434.9,446.9
XS Rating Curve= 0 ,0
Exp/Cntr=0.3,0.1

Type RM Length L Ch R = 1 ,7199.6  ,501,504.8,508.3
XS GIS Cut Line= 3
     1992857.425      160563.644     1993297.017      160031.853
      1993556.13      159914.537
#Sta/Elev= 30
       0 1835.47      50 1829.44      60 1827.58     110 1813.42     130 1809.27
     150 1806.61     160 1805.86     190 1806.03     390 1793.64     470 1790.42
     480 1788.53   495.5 1783.84     500 1782.65   507.5 1782.42     510 1782.35
     550 1783.97     590 1787.06     610 1789.12   699.8    1790     739 1796.13
   748.8    1798   758.6 1800.83     788 1813.41   797.8 1819.59   807.7 1824.98
   846.9 1840.63   866.5 1847.16   895.9 1853.55   935.2 1859.12   974.4  1866.4
#Mann= 3 , 0 , 0
       0     .06       0   495.5    .045       0   507.5     .06       0
Bank Sta=495.5,507.5
XS Rating Curve= 0 ,0
Exp/Cntr=0.3,0.1

Type RM Length L Ch R = 1 ,6694.7  ,702.9,704.6,707.3
XS GIS Cut Line= 3
     1993093.061      160791.233     1993280.553        160675.6
     1993776.164      160211.932
#Sta/Elev= 30
       0 1833.27      67 1826.39   105.4 1824.12   124.5  1822.5   143.7 1820.17
   162.8 1817.08   240.2 1810.04   250.2 1808.38   260.2 1806.12   300.1 1799.77
   320.1 1797.92     350 1793.52     360 1791.12     380 1780.62     381 1780.56
     390 1780.02     393 1780.38   409.9 1782.33   609.5 1787.98   629.5 1789.25
   659.4 1791.91   699.4  1796.6   709.3 1800.35   729.3 1805.63   799.2 1835.52
   809.1 1837.76   819.1 1840.77   829.1 1846.71   849.1 1853.15     899 1874.64
#Mann= 3 , 0 , 0
       0     .06       0     381    .045       0     393     .06       0
Bank Sta=381,393
XS Rating Curve= 0 ,0
Exp/Cntr=0.3,0.1

Type RM Length L Ch R = 1 ,5990    ,388.7,399.9,411.3
XS GIS Cut Line= 3
     1993587.881      161129.319     1993905.618      160871.159
     1994236.222      160628.499
#Sta/Elev= 30
       0 1805.93    49.9  1795.1    59.9 1793.34    79.9 1791.64   139.8 1788.74
   169.8  1787.7   179.7 1786.96   219.7 1781.53   229.7 1780.66   249.6 1780.01
   403.4 1779.96   409.4  1779.9   415.4 1780.76   419.2  1781.3   428.9 1787.42
   438.7 1794.73   448.4 1798.88     468 1803.77   477.7 1806.77   487.5 1811.19
   497.3 1813.69   516.8 1816.05   546.1 1822.41   585.2 1829.96   604.7 1834.71
     634 1839.36   682.8 1852.77   702.3 1860.57   780.4 1884.62   819.5 1898.28
#Mann= 3 , 0 , 0
       0     .06       0   403.4    .045       0   415.4     .06       0
Bank Sta=403.4,415.4
XS Rating Curve= 0 ,0
Exp/Cntr=0.3,0.1

Type RM Length L Ch R = 1 ,5590    ,467.5,471.7,474.7
XS GIS Cut Line= 3
     1993676.005      161264.058       1994129.8      161194.136
     1994528.658      161155.358
#Sta/Elev= 30
       0 1813.21    29.9 1807.85    49.9 1802.05    89.8 1794.42    99.8 1793.19
   329.4 1784.34   379.3 1782.07   409.2 1780.07   453.2    1780   465.2    1780
   488.5 1779.99   498.2 1780.37   517.8 1783.04   527.6 1785.75   537.3 1789.46
   547.1 1795.34   556.9 1798.53   615.5 1814.26   644.9 1819.24   664.4 1823.21
     684 1825.64   693.7 1826.03   703.5  1825.5   742.6 1822.14   771.9  1817.4
   781.7 1815.25   791.5 1811.94     811  1809.7   840.3 1808.98   859.9 1811.38
#Mann= 3 , 0 , 0
       0     .06       0   453.2    .045       0   465.2     .06       0
Bank Sta=453.2,465.2
XS Rating Curve= 0 ,0
Exp/Cntr=0.3,0.1

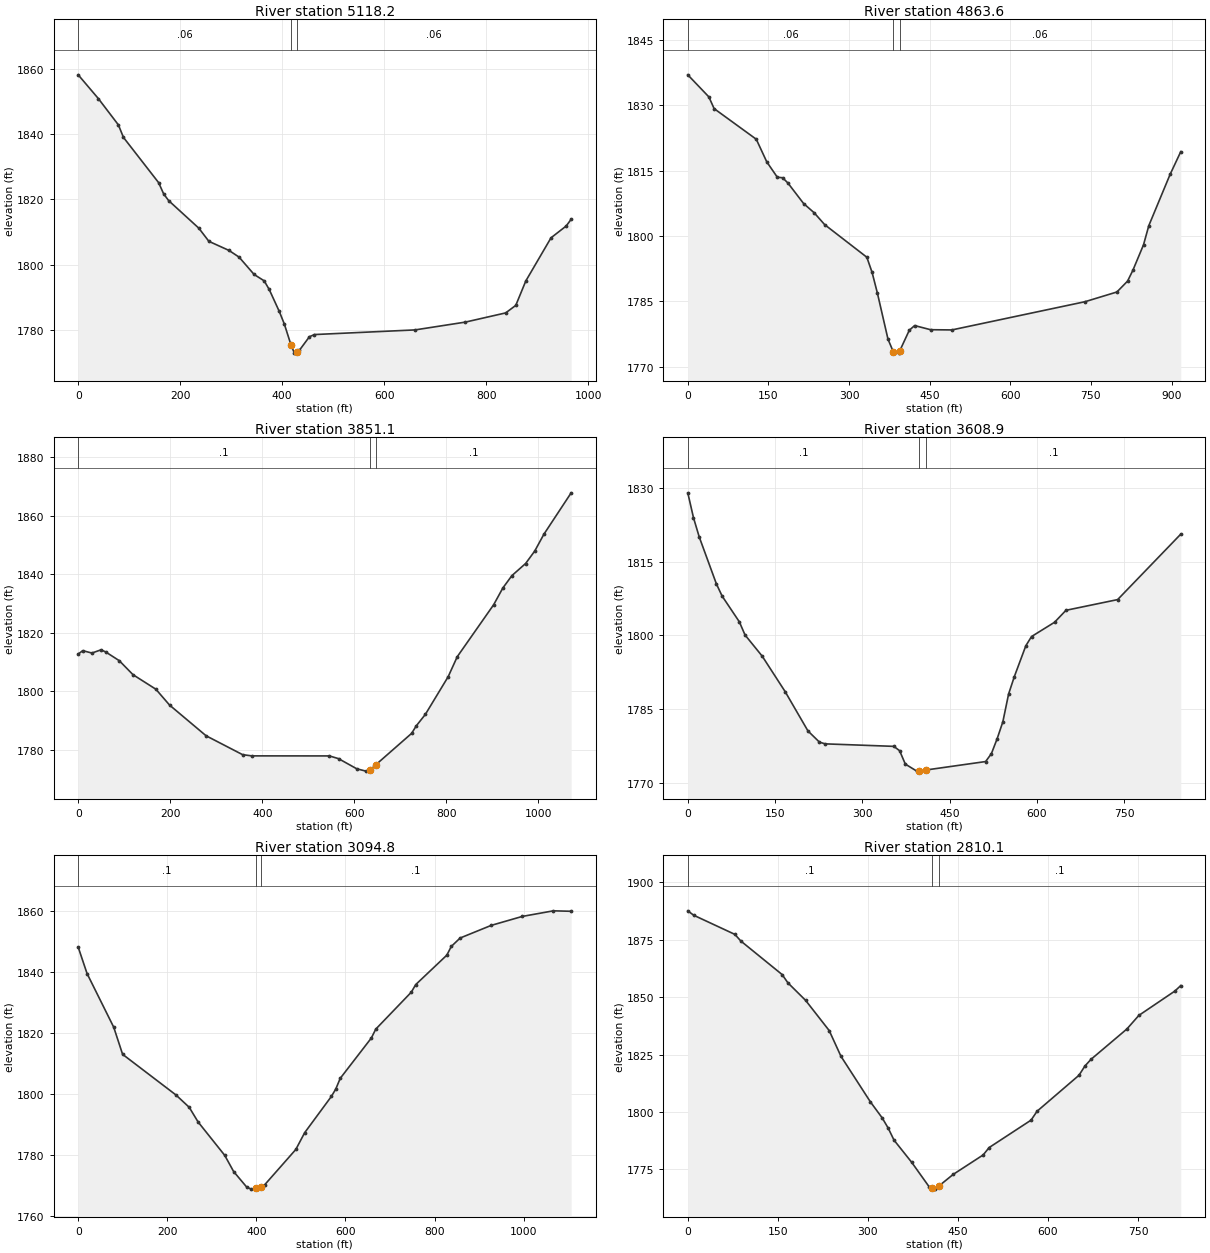
Type RM Length L Ch R = 1 ,5118.2  ,268.9,254.5,240.1
XS GIS Cut Line= 3
     1993629.592      161618.994      1994250.29      161633.812
     1994535.887      161439.424
#Sta/Elev= 30
       0 1858.12    39.4 1850.88    78.8 1842.81    88.7 1838.99   157.7 1825.14
   167.5 1821.72   177.4 1819.64   236.5 1811.22   256.2  1807.2   295.6 1804.42
   315.4 1802.37   344.9 1797.06   364.6 1795.12   374.5 1792.47   394.2 1785.76
   404.1 1781.91   417.2  1775.5   423.8 1773.01   429.2 1773.48   433.6 1773.87
   453.3 1778.03   463.2 1778.69   660.4 1780.11   759.1  1782.5     838 1785.31
   857.8 1787.61   877.5 1795.09   926.9 1808.28   956.5 1811.87   966.4 1813.95
#Mann= 3 , 0 , 0
       0     .06       0   417.2    .045       0   429.2     .06       0
Bank Sta=417.2,429.2
XS Rating Curve= 0 ,0
Exp/Cntr=0.3,0.1

Type RM Length L Ch R = 1 ,4863.6  ,995.4,1012.4,1016.4
XS GIS Cut Line= 3
      1993837.04      162058.586     1994136.687      161872.541
     1994585.684      161530.598
#Sta/Elev= 30
       0 1836.95    39.2 1831.89      49  1829.2   127.4 1822.18     147 1816.98
   166.6 1813.46   176.4 1813.35   186.2 1812.15   215.5 1807.43   235.1 1805.32
   254.7 1802.59   333.1 1795.12   342.9 1791.63   352.7 1786.91   372.5 1776.31
   382.2 1773.48   392.3 1773.13   394.2 1773.62   412.1 1778.38     422 1779.45
   451.7  1778.5   491.3 1778.45   738.9 1784.92   798.3 1787.15   818.1 1789.64
     828 1792.12   847.8 1797.97   857.7 1802.38   897.3 1814.13   917.1 1819.33
#Mann= 3 , 0 , 0
       0     .06       0   382.2    .045       0   394.2     .06       0
Bank Sta=382.2,394.2
XS Rating Curve= 0 ,0
Exp/Cntr=0.3,0.1

Type RM Length L Ch R = 1 ,3851.1  ,241,242.2,242
XS GIS Cut Line= 3
     1994199.251      162582.145      1994915.44      162239.691
      1995169.55       162129.12
#Sta/Elev= 30
       0 1812.74     9.9 1813.89    29.8 1813.08    49.6 1814.18    59.5 1813.48
    89.3 1810.46   119.1 1805.67   168.7 1800.71   198.5 1795.28   277.8 1784.78
   357.2 1778.31   377.1  1777.9   545.8 1777.88   565.6 1776.95   605.3 1773.47
   625.2 1772.68     634 1773.04     646 1774.78   724.4  1785.6   734.3 1788.13
   754.2 1792.09   803.8 1804.99   823.5 1811.82   902.7 1829.63   922.5 1835.32
   942.3 1839.58     972 1843.71   991.8 1847.96  1011.6 1853.69    1071 1867.89
#Mann= 3 , 0 , 0
       0      .1       0     634    .045       0     646      .1       0
Bank Sta=634,646
XS Rating Curve= 0 ,0
Exp/Cntr=0.3,0.1

Type RM Length L Ch R = 1 ,3608.9  ,502.7,514.1,526.5
XS GIS Cut Line= 3
     1994437.712      162698.811     1994806.371      162534.956
     1995199.346      162328.553
#Sta/Elev= 30
       0 1829.03     9.8 1823.97    19.7 1820.04    49.2 1810.49      59 1808.02
    88.6 1802.78    98.4  1800.1   127.9 1795.79   167.3 1788.58   206.6 1780.56
   226.3 1778.29   236.2 1777.94   354.2 1777.43   364.1 1776.54   373.9 1773.82
   393.6 1772.39   397.4 1772.42   409.4 1772.62   511.9 1774.34   521.8 1775.94
   531.7 1778.98   541.5 1782.42   551.4 1788.09   561.3 1791.64     581  1797.9
   590.8 1799.78   630.3 1802.68     650 1805.12   738.8  1807.3   847.3 1820.62
#Mann= 3 , 0 , 0
       0      .1       0   397.4    .045       0   409.4      .1       0
Bank Sta=397.4,409.4
XS Rating Curve= 0 ,0
Exp/Cntr=0.3,0.1

Type RM Length L Ch R = 1 ,3094.8  ,284,284.5,286.4
XS GIS Cut Line= 2
     1994514.447      162844.392     1995618.458      162922.952
#Sta/Elev= 30
       0 1848.19    19.9 1839.53    79.8 1821.93    99.7 1813.06   219.4 1799.75
   249.3 1795.69   269.2 1790.89     329 1779.95     349 1774.64   378.9 1769.45
   388.9 1768.88     399  1769.1     411 1769.59   418.8 1770.32   488.6 1781.88
   508.5 1787.38   568.4 1799.25   578.3 1801.68   588.3 1805.18   658.1 1818.39
   668.1 1821.31   747.8 1833.41   757.8 1835.91   827.6 1845.55   837.6  1848.4
   857.5 1851.17   927.3 1855.31   997.1 1858.25  1066.9 1860.08  1106.8 1859.93
#Mann= 3 , 0 , 0
       0      .1       0     399    .045       0     411      .1       0
Bank Sta=399,411
XS Rating Curve= 0 ,0
Exp/Cntr=0.3,0.1

Type RM Length L Ch R = 1 ,2810.1  ,398.3,397.7,393.9
XS GIS Cut Line= 3
     1994520.461      163113.984     1994930.894      163153.273
     1995334.147      163221.622
#Sta/Elev= 30
       0 1887.63     9.8 1885.72    78.5 1877.36    88.4 1874.47   157.1 1859.88
   166.9 1856.23   196.3 1848.62   235.6 1835.46   255.2 1824.25   304.3 1804.37
     324 1797.37   333.8    1793   343.6 1787.72     373 1778.07   402.5 1767.25
   406.3 1766.91   412.3 1766.38   418.3 1767.74   442.2  1772.8   492.1 1781.28
   502.1  1784.5   571.9 1796.44   581.9 1800.31   651.7 1815.98   661.7 1820.04
   671.7 1822.91   731.5 1836.14   751.5 1842.07   811.3 1852.64   821.3 1855.06
#Mann= 3 , 0 , 0
       0      .1       0   406.3    .045       0   418.3      .1       0
Bank Sta=406.3,418.3
XS Rating Curve= 0 ,0
Exp/Cntr=0.3,0.1

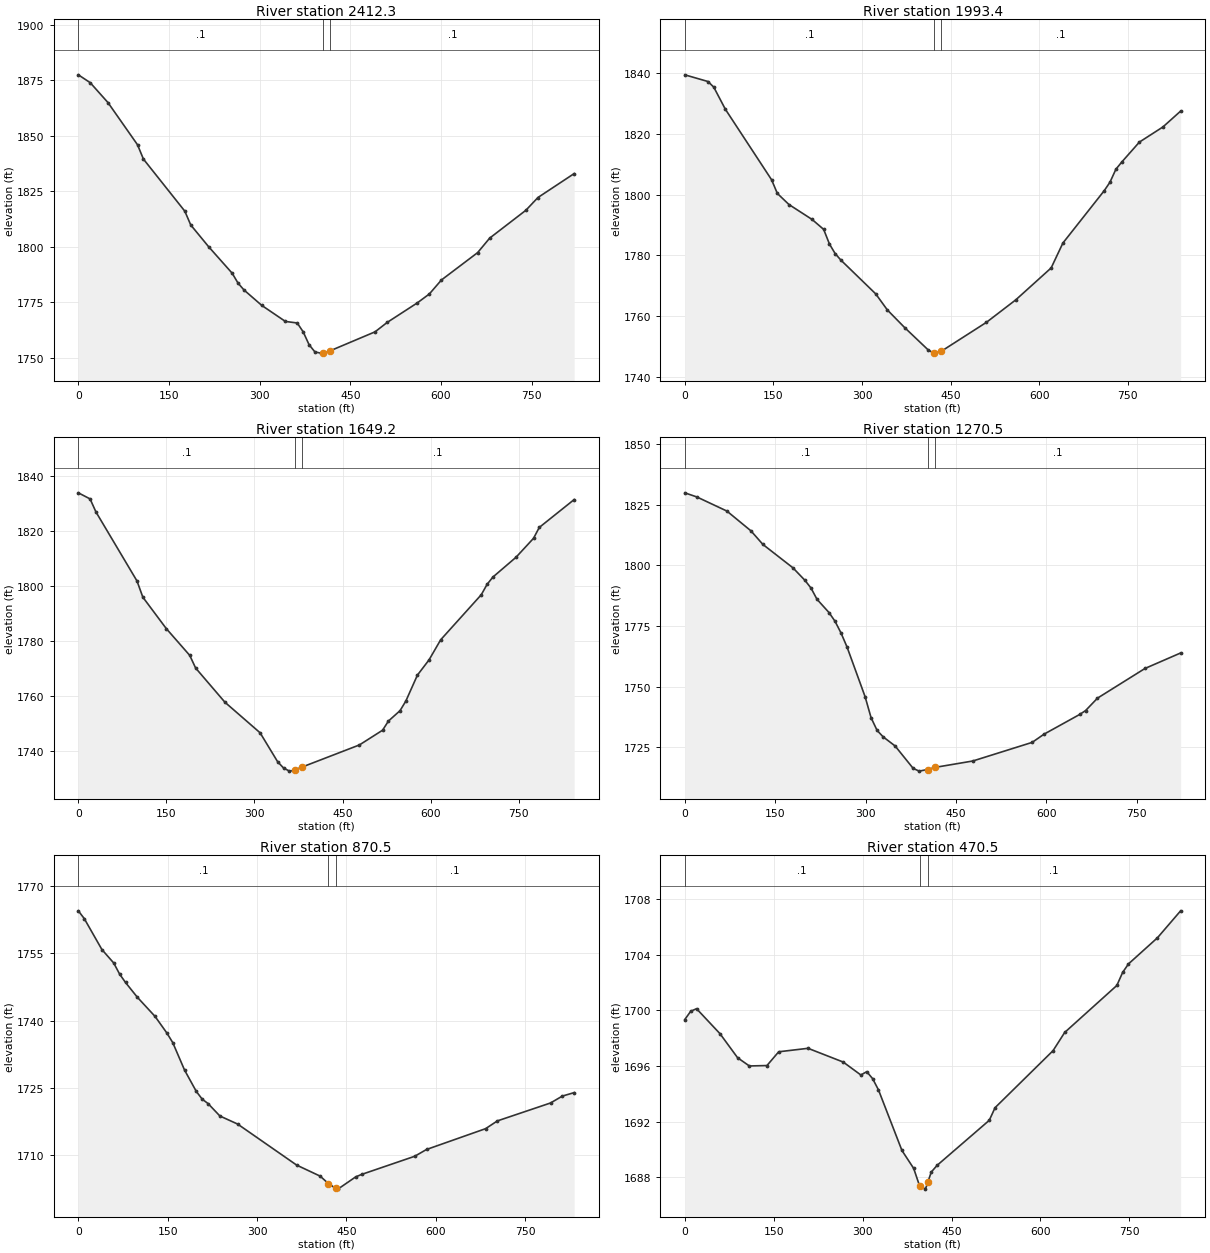
Type RM Length L Ch R = 1 ,2412.3  ,430.6,418.9,406.9
XS GIS Cut Line= 3
     1994502.893      163520.371      1994913.24      163546.019
     1995322.376      163538.299
#Sta/Elev= 30
       0 1877.45    19.6 1873.93      49 1864.97    97.9 1845.97   107.7 1839.52
   176.2 1816.07     186 1809.86   215.4 1800.13   254.5 1788.15   264.3 1783.66
   274.1 1780.59   303.5 1773.65   342.6 1766.43   362.2 1765.73     372 1761.76
   381.8 1755.95   391.6 1752.66   401.4 1752.16   405.1 1752.32   417.1 1753.26
     491 1761.75     511 1765.98   560.9 1774.78   580.8 1778.79   600.8 1785.09
   660.7 1797.41   680.6 1803.93   740.5 1816.47   760.5 1822.22   820.4 1832.99
#Mann= 3 , 0 , 0
       0      .1       0   405.1    .045       0   417.1      .1       0
Bank Sta=405.1,417.1
XS Rating Curve= 0 ,0
Exp/Cntr=0.3,0.1

Type RM Length L Ch R = 1 ,1993.4  ,331.3,344.2,359.1
XS GIS Cut Line= 3
     1994629.512      164107.911     1995011.264      163907.956
     1995349.143      163678.525
#Sta/Elev= 30
       0 1839.42    39.2 1837.22      49 1835.38    68.6 1828.11   146.9 1804.88
   156.7 1800.37   176.3 1796.73   215.5 1791.81   235.1 1788.54   244.9 1783.72
   254.6 1780.56   264.4  1778.4   323.2 1767.32   342.8 1762.05   372.2 1756.22
   411.4 1748.98   421.2 1747.81   422.2 1747.84   434.2 1748.42   510.6 1757.94
   560.4 1765.36   620.2 1775.85   640.1 1784.05   709.9 1801.24   719.8 1804.07
   729.8 1808.34   739.8 1810.72   769.6 1817.28   809.5 1822.27   839.4 1827.48
#Mann= 3 , 0 , 0
       0      .1       0   422.2    .045       0   434.2      .1       0
Bank Sta=422.2,434.2
XS Rating Curve= 0 ,0
Exp/Cntr=0.3,0.1

Type RM Length L Ch R = 1 ,1649.2  ,368.9,378.6,385.2
XS GIS Cut Line= 3
     1994650.198      164209.985     1995067.444      164253.143
     1995464.579      164404.742
#Sta/Elev= 30
       0 1833.95      20 1831.74      30    1827    99.9 1801.91   109.9 1796.01
   149.8  1784.6   189.8 1774.85   199.8 1770.26   249.7 1757.83   309.6 1746.72
   339.6 1736.16   349.6 1733.92   359.6 1732.78   368.5  1733.1   380.5 1734.21
   478.8  1742.3   518.3 1747.66   528.2 1750.98     548 1754.76   557.9 1758.26
   577.6 1767.68   597.4 1773.22   617.2 1780.52   686.4 1796.91   696.3 1800.68
   706.2 1803.33   745.7 1810.55   775.4 1817.42   785.2 1821.37   844.6  1831.5
#Mann= 3 , 0 , 0
       0      .1       0   368.5    .045       0   380.5      .1       0
Bank Sta=368.5,380.5
XS Rating Curve= 0 ,0
Exp/Cntr=0.3,0.1

Type RM Length L Ch R = 1 ,1270.5  ,399.2,399.9,408.2
XS GIS Cut Line= 3
     1994572.964      164386.077     1994920.508      164601.221
     1995300.661      164764.586
#Sta/Elev= 30
       0  1829.9    19.9 1828.21    69.8 1822.39   109.7 1814.24   129.6 1808.63
   179.4    1799   199.4 1793.82   209.4 1790.65   219.3 1786.04   239.3 1780.55
   249.2 1776.98   259.2 1772.13   269.2 1766.33   299.1  1745.9     309 1737.25
     319 1732.01     329 1729.37   348.9  1725.6   378.8 1716.38   388.8 1715.24
   402.7  1715.9   414.7 1716.76   477.7 1719.41   576.2 1727.08   595.9 1730.46
     655 1738.58   664.9  1740.2   684.6 1745.31   763.4 1757.54   822.5 1763.92
#Mann= 3 , 0 , 0
       0      .1       0   402.7    .045       0   414.7      .1       0
Bank Sta=402.7,414.7
XS Rating Curve= 0 ,0
Exp/Cntr=0.3,0.1

Type RM Length L Ch R = 1 ,870.5   ,396,399.6,399.4
XS GIS Cut Line= 3
       1994456.1      164736.553     1994810.318      164973.049
     1995091.478      165266.777
#Sta/Elev= 30
       0 1764.48     9.9 1762.76    39.6 1755.85    59.4 1752.86    69.3 1750.39
    79.2 1748.52      99 1745.24   128.8 1740.96   148.6 1737.27   158.5 1735.13
   178.3 1729.02   198.1 1724.24     208 1722.52   217.9 1721.53   237.7 1718.77
   267.4 1716.98   366.5 1707.84   406.1 1705.37   419.9 1703.72   431.9 1702.68
   435.8 1702.48   465.6  1705.2   475.5 1705.75   564.8  1709.8   584.6 1711.31
   683.8 1715.95   703.6 1717.68   792.8 1721.67   812.7 1723.21   832.5 1723.98
#Mann= 3 , 0 , 0
       0      .1       0   419.9    .045       0   431.9      .1       0
Bank Sta=419.9,431.9
XS Rating Curve= 0 ,0
Exp/Cntr=0.3,0.1

Type RM Length L Ch R = 1 ,470.5   ,482.4,470.5,457.8
XS GIS Cut Line= 3
     1994192.157      164949.192     1994508.334      165219.293
     1994818.063      165503.854
#Sta/Elev= 30
       0 1699.34     9.9 1699.93    19.8 1700.12    59.4 1698.32    89.1 1696.59
   108.9    1696   138.6 1696.03   158.4 1697.02   207.9 1697.27   267.3 1696.28
     297 1695.35   306.9 1695.59   316.8 1695.09   326.7 1694.28   366.3 1689.92
   386.1 1688.63     396 1687.38   405.9 1687.14   409.8 1687.62   415.8 1688.37
   425.6 1688.85   513.6 1692.09   523.4    1693   621.2  1697.1   640.8 1698.41
   728.8 1701.79   738.6 1702.73   748.4 1703.34   797.3 1705.22   836.4 1707.16
#Mann= 3 , 0 , 0
       0      .1       0     396    .045       0   409.8      .1       0
Bank Sta=396,409.8
XS Rating Curve= 0 ,0
Exp/Cntr=0.3,0.1

Chan Stop Cuts=-1
Use User Specified Reach Order=0
Composite Channel Slope=5